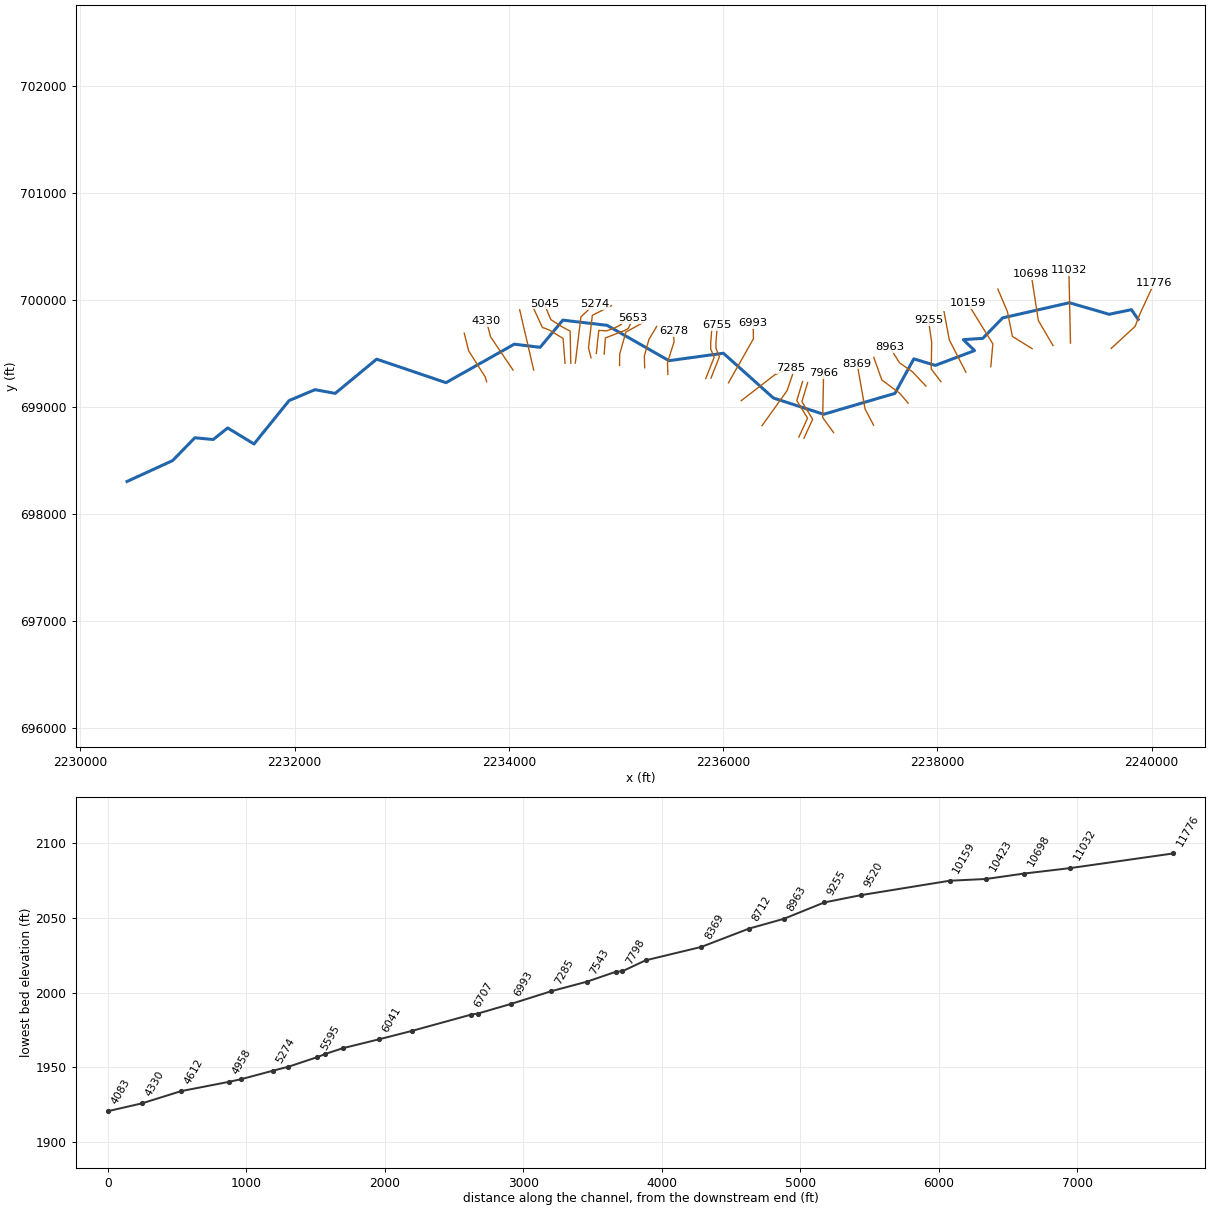
--- BROOKRN.prj (project) ---

Proj Title=BROOKRN
Current Plan=p01
Default Exp/Contr=0,0
English Units
Geom File=g01
Flow File=f01
Plan File=p01
BEGIN DESCRIPTION:
----------MODEL BY WSP USA 2022----------
AFH study
Randolph County, WV
HEC-RAS Version: RAS 6.2
Vertical Datum: NAVD88
Projection: NAD 1983 StatePlane West Virginia S FIPS 4702 (US Feet)
Terrain: 1-meter LIDAR (FEMA Region III 3DEP collected 2016-2018)
Land Use: 2019 NLCD
Hydrologic Method:
WV SIR2010-5033 regression equations
Additional Model Notes:
Potential coincident peak situation; DA ratio is 0.6
However, tie-in is still achieved with normal depth BC
END DESCRIPTION:
DSS Export Rating Curves= 0
DSS Export Rating Curve Sorted= 0
DSS Export Volume Flow Curves= 0
DXF OffsetX= 0
DXF OffsetY= 0
DXF ScaleX= 0
DXF ScaleY= 0

--- BROOKRN.p01 (plan) ---

Plan Title=Floodplain
Program Version=6.20
Short Identifier=Floodplain
Geom File=g01
Flow File=f01
Subcritical Flow
K Sum by GR= 0
Std Step Tol= 0.01
Critical Tol= 0.01
Num of Std Step Trials= 20
Max Error Tol= 0.3
Flow Tol Ratio= 0.001
Split Flow NTrial= 30
Split Flow Tol= 0.02
Split Flow Ratio= 0.02
Log Output Level= 0
Friction Slope Method= 1
Unsteady Friction Slope Method= 2
Unsteady Bridges Friction Slope Method= 1
Parabolic Critical Depth
Global Vel Dist= 0 , 0 , 0
Global Log Level= 0
CheckData=True
Encroach Param=-1 ,0,0, 0
Mapping Interval=1HOUR
Computation Time Step Use Courant=        0
Computation Time Step Use Time Series=    0
Computation Time Step Count To Double=0
Computation Time Step Max Doubling=0
Computation Time Step Max Halving=0
Computation Time Step Residence Courant=0
Run HTab= 0
Run UNet= 0
Run Sediment= 0
Run PostProcess= 0
Run WQNet= 0
Run RASMapper=-1
UNET Theta= 0
UNET Theta Warmup= 0
UNET ZTol= 0
UNET ZSATol= 0
UNET MxIter= 0
UNET Max Iter WO Improvement= 0
UNET MaxInSteps= 0
UNET DtIC= 0
UNET DtMin= 0
UNET MaxCRTS= 0
UNET WFStab= 0
UNET SFStab= 0
UNET WFX= 1
UNET SFX= 1
UNET Gravity=32.174
UNET 1D Methodology=Finite Difference
UNET DSS MLevel= 1
UNET Pardiso=0
UNET DZMax Abort= 0
UNET Use Existing IB Tables= 0
UNET Froude Reduction=False
UNET Froude Limit= 0
UNET Froude Power= 0
UNET D1 Cores= 0
UNET WindReference=Eulerian
UNET WindDragFormulation=Hsu (1988)
UNET D2 Coriolis=0
UNET D2 Cores= 0
UNET D2 Theta= 1
UNET D2 Theta Warmup= 1
UNET D2 Z Tol= 0.01
UNET D2 Volume Tol= 0.01
UNET D2 Max Iterations= 20
UNET D2 Equation= 0
UNET D2 RampUpFraction=0.1
UNET D2 TimeSlices= 1
UNET D2 Turbulence Formulation=Non-Conservative (original)
UNET D2 Eddy Viscosity=0.3
UNET D2 Transverse Eddy Viscosity=0.1
UNET D2 Smagorinsky Mixing=0
UNET D2 BCVolumeCheck=0
UNET D2 Cores=0
UNET D2 SolverType=PARDISO (Direct)
UNET D2 Minimum Iterations= 2147483647
UNET D2 Maximum Iterations= 2147483647
UNET D2 Restart Number= 10
UNET D2 Relaxation Coeff=1.3
UNET D2 SOR Precondition Iterations= 10
UNET D2 ILUT Maximum Fill= 8
UNET D2 ILUT Tolerance=1E-08
UNET D1D2 MaxIter= 0
UNET D1D2 ZTol=0.01
UNET D1D2 QTol=0.1
UNET D1D2 MinQTol=1
Write IC File= 0
Write IC File at Fixed DateTime=0
Write IC File at Sim End=0
Echo Input=False
Echo Parameters=False
Echo Output=False
Write Detailed= 0
HDF Write Warmup=0
HDF Write Time Slices=0
HDF Flush=0
HDF Compression= 1
HDF Chunk Size= 1
HDF Spatial Parts= 1
HDF Use Max Rows=0
HDF Fixed Rows= 1
Calibration Method= 0
Calibration Iterations= 20
Calibration Max Change=0.05
Calibration Tolerance=0.2
Calibration Maximum=1.5
Calibration Minimum=0.5
Calibration Optimization Method= 1
WQ AD Non Conservative
WQ ULTIMATE=-1
WQ Max Comp Step=1HOUR
WQ Output Interval=15MIN
WQ Output Selected Increments= 0
WQ Output face flow=0
WQ Output face velocity=0
WQ Output face area=0
WQ Output face dispersion=0
WQ Output cell volume=0
WQ Output cell surface area=0
WQ Output cell continuity=0
WQ Output cumulative cell continuity=0
WQ Output face conc=0
WQ Output face dconc_dx=0
WQ Output face courant=0
WQ Output face peclet=0
WQ Output face adv mass=0
WQ Output face disp mass=0
WQ Output cell mass=0
WQ Output cell source sink temp=0
WQ Output nsm pathways=0
WQ Output nsm derived pathways=0
WQ Create Restart=0
WQ Fixed Restart=0
WQ System Summary=0
WQ Write To DSS=0
Sorting and Armoring Iterations= 10
XS Update Threshold= 0.02
Bed Roughness Predictor= 0
Hydraulics Update Threshold= 0.02
Energy Slope Method= 1
Volume Change Method= 1
Sediment Retention Method= 0
Sediment TS Multiplier= 1
Warm Up Method= 0
XS Weighting Method= 0
Number of US Weighted Cross Sections= 1
Number of DS Weighted Cross Sections= 1
Upstream XS Weight=0
Main XS Weight=1
Downstream XS Weight=0
Number of DS XS's Weighted with US Boundary= 1
Upstream Boundary Weight= 1
Weight of XSs Associated with US Boundary= 0
Number of US XS's Weighted with DS Boundary= 1
Downstream Boundary Weight= 0.5
Weight of XSs Associated with DS Boundary= 0.5
Percentile Method= 0
Sediment Output Level= 3
Mass or Volume Output= 0
Output Increment Type= 1
Profile and TS Output Increment= 1
Transport Output Increment 1
XS Output Flag= 0
XS Output Increment= 10
Read HDF5 Sediment Hotstart= 0
Sediment Hotstart Type= 0
Write Gradation File= 0
Read Gradation Hotstart= 0
Write HDF5 File= 1
Write Binary Output= 1
Write DSS Sediment File= 0
DSS Sediment Output Type= 1
SV Curve= 0
Specific Gage Flag= 0
Subcell Erosion Methods= 0
Subcell Deposition Methods= 0
Advection Scheme= 1
Matrix Solver= 0
Implicit Weighting Factor= 1
Maximum Outer Loop Convergence Iterations= 5
Convergence Maximum Absolute= 0.001
Convergence RMSE= 0.0001
Grain Fractions Max Abs Error= 0.001
Max Subgrid Regions= 1
Max Subgrid Length Scale= 3.402823E+38
Initial Layer Thickness= 3.402823E+38
Min Layer Thickness= 3.402823E+38
Max Layer Thickness= 3.402823E+38
Number of Layers= 5

--- BROOKRN.f01 (steady flow) ---

Flow Title=Flow
Program Version=6.20
Number of Profiles= 1
Profile Names=P100yr
River Rch & RM=BROOKRN,Main,11776
     342
River Rch & RM=BROOKRN,Main,8369
     383
River Rch & RM=BROOKRN,Main,6755
     494
River Rch & RM=BROOKRN,Main,5387
     647
River Rch & RM=BROOKRN,Main,2573
     727
Boundary for River Rch & Prof#=BROOKRN,Main            , 1
Up Type= 0
Dn Type= 3
Dn Slope=0.01014
DSS Import GetInterval= 0
DSS Import GetPeak= 0
DSS Import FillOption= 0

--- BROOKRN.g01 (geometry) ---

Geom Title=Geometry
Program Version=6.20

River Reach=BROOKRN         ,Main
Reach XY= 30
     2239873.793      699817.211     2239810.391      699907.991
  2239602.357541699865.118144452     2239231.312      699972.976
       2238608.5       699831.31     2238423.847      699640.531
     2238241.787      699628.125      2238346.07      699525.944
     2237979.941      699387.574     2237779.507      699448.772
     2237602.944      699126.116      2236937.58      698931.064
     2236468.569      699083.147     2236001.968      699501.319
     2235493.981      699431.874     2234915.509      699762.082
     2234503.566      699810.278     2234291.334        699556.5
     2234050.522      699586.007     2233412.792      699226.435
     2232765.432      699445.9062232378.46292843 699126.34578595
       2232189.9      699160.818     2231948.117       699058.98
     2231620.799      698653.568     2231375.101      698803.449
     2231240.233      698695.313     2231068.451      698711.507
     2230860.652      698498.136     2230435.475       698303.49

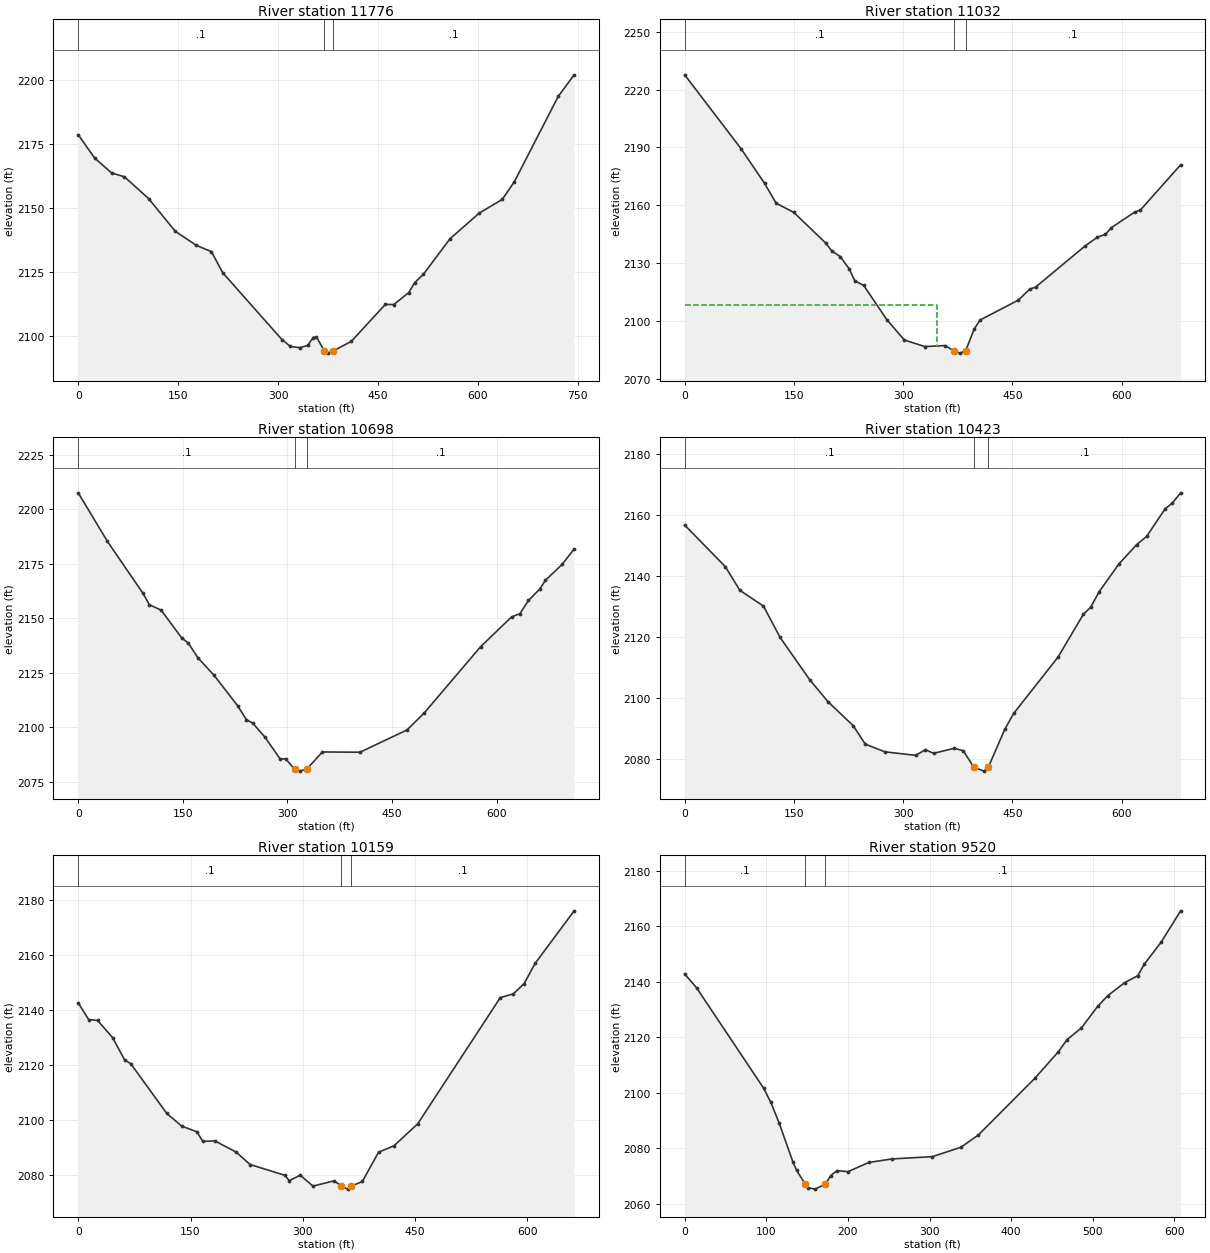
Type RM Length L Ch R = 1 ,11776   ,737.6,744.1,742.6
XS GIS Cut Line= 4
2239621.16433754699545.5058503352239844.76154632699751.935205177
2239889.38564116 699867.012777072240021.91118572700154.591357599
#Sta/Elev= 30
       0 2178.78    24.5 2169.68      50 2163.81    69.4 2162.29   105.7 2153.75
   145.6 2140.99   177.4 2135.44     200 2132.97     217 2124.72   305.7 2098.59
   318.5 2095.88   332.6 2095.39   344.3 2096.29   352.8 2099.37   357.4 2099.67
  369.35 2094.14   374.3 2093.26   382.9 2094.15   409.9 2097.86     461 2112.33
   473.7 2112.29   496.2 2116.98     505 2120.85   518.2 2124.15   558.1 2138.05
   601.9 2148.06   636.5 2153.45   654.6 2160.34   720.5 2193.77   744.4 2202.21
#Mann= 3 ,0,0
       0      .1       0  369.35    .045       0   382.9      .1       0
Bank Sta=369.35,382.9
XS Rating Curve= 0 ,0
Exp/Cntr=0.3,0.1

Type RM Length L Ch R = 1 ,11032   ,332.8,334.2,334.4
XS GIS Cut Line= 2
2239241.81465731699595.5441244792239226.71546556700276.380406977
#Sta/Elev= 30
       0 2227.65    77.7 2189.21   109.7 2171.41   125.7 2161.05   149.7 2156.42
   193.7 2140.46   201.7 2136.53   213.7 2133.41   225.7 2127.23   233.7 2120.87
   245.9 2118.48   277.7 2100.71   301.7 2090.22   329.7 2086.85   357.7 2087.34
   369.7 2084.59   377.7 2083.43   385.7 2084.57   397.7 2096.04   405.7  2100.6
   458.3 2110.92   473.8  2116.6   481.8 2117.62   549.8 2138.96   566.8 2143.52
   577.8    2145   585.8 2148.43   617.8 2156.48   625.8  2157.6     681 2181.02
#Mann= 3 ,-1,0
       0      .1       0   369.7    .045       0   385.7      .1       0
#XS Ineff= 2 , 0
          346.71 2108.41
Permanent Ineff=
       F       F
Bank Sta=369.7,385.7
XS Rating Curve= 0 ,0
Exp/Cntr(USF)=0,0
Exp/Cntr=0.3,0.1

Type RM Length L Ch R = 1 ,10698   ,274.4,275,275.6
XS GIS Cut Line= 3
2239078.87462644699573.1789056642238941.74651228699806.667316255
2238874.48647631700241.935834763
#Sta/Elev= 30
       0 2207.43    41.7 2185.25    92.8 2161.36   102.1 2156.07   118.9 2153.63
   148.4 2140.86   157.7 2138.57   171.6 2131.81   194.9 2123.68   228.5 2109.79
   241.2  2103.4   250.5 2101.71   267.9 2095.29   289.5 2085.39   297.6 2085.38
   310.2 2080.72   317.8 2079.76   328.12080.794   350.2 2088.56   404.1 2088.43
   471.6 2098.68   495.9 2106.33   576.9 2136.79   621.4  2150.5   633.5 2152.02
   645.7 2158.06   661.9 2163.29     670 2167.27   694.3 2174.73   711.2 2181.68
#Mann= 3 ,-1,0
       0      .1       0   310.2    .045       0   328.1      .1       0
Bank Sta=310.2,328.1
XS Rating Curve= 0 ,0
Exp/Cntr(USF)=0,0
Exp/Cntr=0.3,0.1

Type RM Length L Ch R = 1 ,10423   ,259.6,263.1,267
XS GIS Cut Line= 4
2238883.68325674699544.2159105822238699.74764816699658.146175597
2238653.07741912699890.1246670132238563.85492242700100.140697703
#Sta/Elev= 30
       0 2156.73    55.9 2143.08    75.9 2135.33   108.2  2130.2     131 2119.95
   171.8 2106.06     197 2098.83   231.7 2090.97     248 2084.98     275 2082.46
   317.4 2081.29   330.7 2083.15   341.9 2081.96   370.4 2083.62   382.7 2082.78
  397.19 2077.41   411.2 2076.13     417  2077.4   439.8 2089.87     452 2095.07
   512.8 2113.47   547.6  2127.5   557.6 2129.81   569.3 2134.88   596.3 2143.95
   620.7  2150.3   634.5 2152.99   659.9 2162.06   669.3  2163.8   681.2 2167.29
#Mann= 3 ,0,0
       0      .1       0  397.19    .045       0     417      .1       0
Bank Sta=397.19,417
XS Rating Curve= 0 ,0
Exp/Cntr(USF)=0,0
Exp/Cntr=0.3,0.1

Type RM Length L Ch R = 1 ,10159   ,634.3,639.4,626
XS GIS Cut Line= 3
2238497.96754024699375.3794937532238517.18469338699588.140832034
2238281.08824057699969.738587143
#Sta/Elev= 30
       0  2142.7    13.9 2136.63    25.9 2136.29      46 2130.02    62.1 2121.88
    70.1  2120.6   118.3 2102.47   138.4 2097.84   158.4 2095.82   166.5 2092.31
   182.5 2092.49   210.7 2088.46   229.6  2083.9     276 2079.98   281.9 2078.05
   296.5 2080.01   313.6 2076.06   341.8 2077.96  351.53 2076.05     360 2074.95
   364.92076.056   379.5 2077.73   401.1 2088.36   421.8 2090.73   453.4 2098.69
   563.8 2144.61   581.3 2145.97   595.7 2149.73   610.3 2157.06   662.4 2176.16
#Mann= 3 ,0,0
       0      .1       0  351.53    .045       0   364.9      .1       0
Bank Sta=351.53,364.9
XS Rating Curve= 0 ,0
Exp/Cntr(USF)=0,0
Exp/Cntr=0.3,0.1

Type RM Length L Ch R = 1 ,9520    ,269,264.8,259.5
XS GIS Cut Line= 3
2238265.98904883 699323.218649532238110.87916995699625.202484509
2238061.46363332699888.752013217
#Sta/Elev= 30
       0 2142.86    14.7  2137.8    96.6 2101.75   105.6 2096.53   115.7 2089.16
   132.6 2075.11   137.1 2072.08   147.92067.031   151.3 2065.81   159.6 2065.31
   172.1 2067.05   179.1 2070.22   186.6 2071.97   200.1 2071.61   225.6 2074.92
     254 2076.19   303.5 2077.02   338.5 2080.41   359.8 2084.82     429 2105.25
   457.5 2114.71   468.6 2119.22     486 2123.39   506.3 2131.31   518.5 2135.07
   538.9 2139.69   555.2 2142.25   563.3 2146.47   583.6 2154.24   607.6  2165.6
#Mann= 3 ,-1,0
       0      .1       0   147.9    .045       0   172.1      .1       0
Bank Sta=147.9,172.1
XS Rating Curve= 0 ,0
Exp/Cntr(USF)=0,0
Exp/Cntr=0.3,0.1

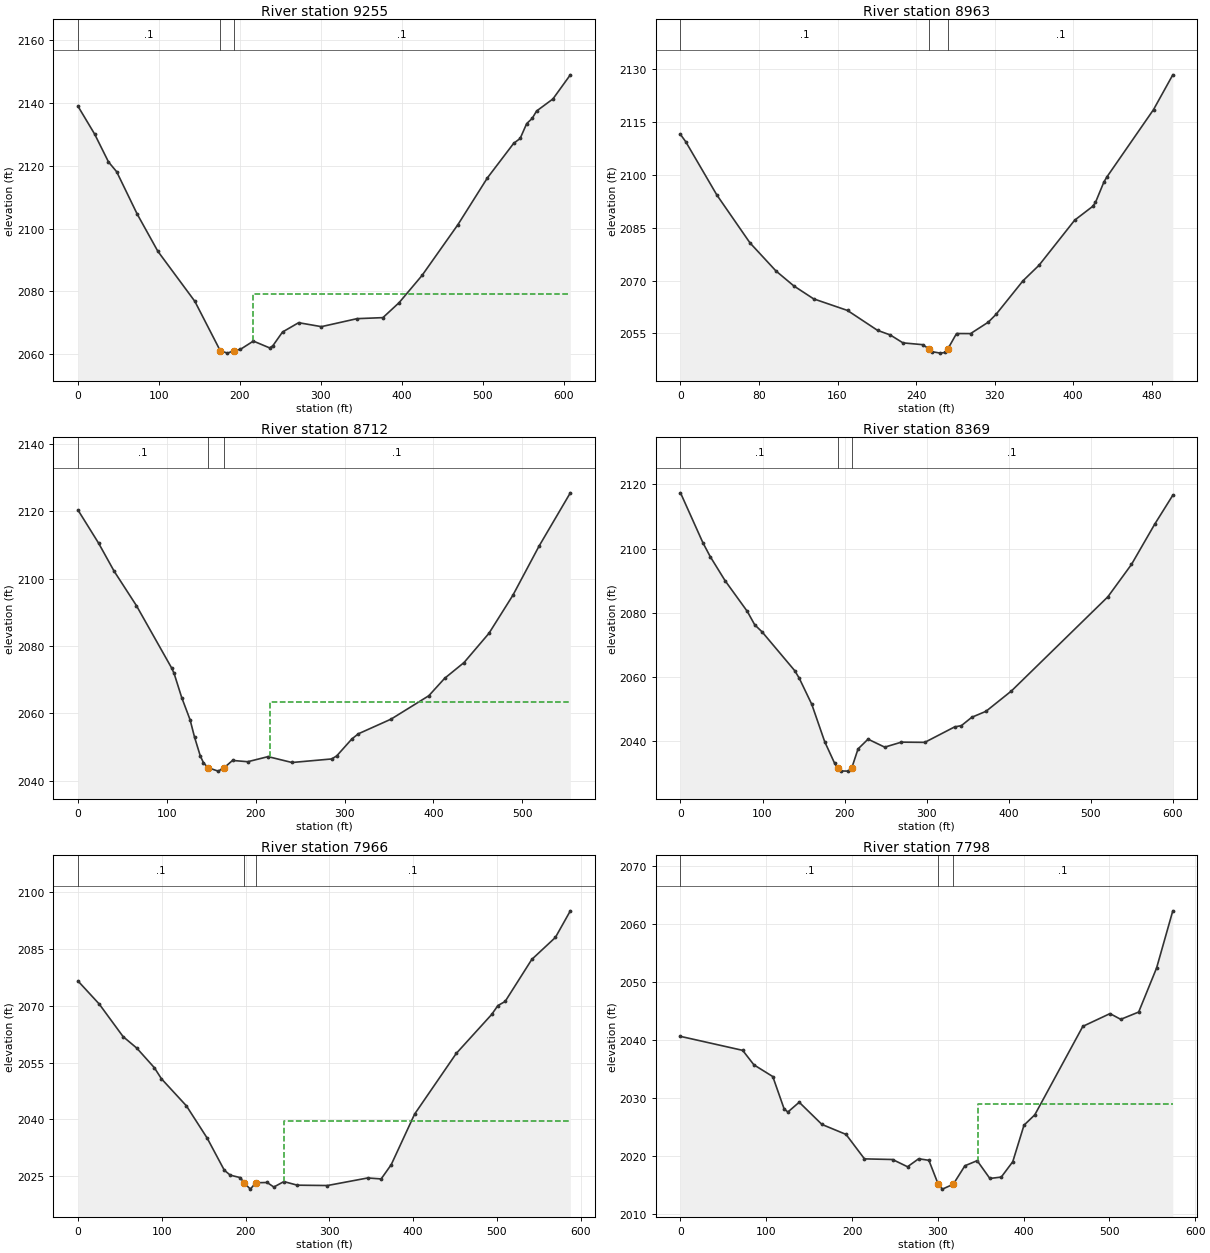
Type RM Length L Ch R = 1 ,9255    ,279.9,292.3,298.9
XS GIS Cut Line= 4
2238032.63790361699235.3688066272237942.04275312699353.417033027
2237946.16071451699603.2400237832237915.96233101699810.510746882
#Sta/Elev= 30
       0 2138.89    20.5 2130.07    37.6 2121.22    47.7  2118.1      73 2104.66
    98.6 2092.79   144.3 2076.87   175.7 2061.15   184.6  2060.4   192.6 2061.17
   200.6 2061.61   216.6 2064.23   236.6 2062.07   240.6 2062.73   252.6 2067.12
   272.5 2070.08   300.6 2068.82   344.6 2071.36   376.6 2071.69   396.6 2076.45
   424.9  2085.1   469.2 2101.25   505.7 2116.15   538.1 2127.12   546.1 2128.67
   554.2  2133.4   560.9 2135.03   566.4  2137.4   586.6 2141.24   608.1 2148.91
#Mann= 3 ,0,0
       0      .1       0   175.7    .045       0   192.6      .1       0
#XS Ineff= 2 , 0
                          215.81         2079.14
Permanent Ineff=
       F       F
Bank Sta=175.7,192.6
XS Rating Curve= 0 ,0
Exp/Cntr(USF)=0,0
Exp/Cntr=0.3,0.1

Type RM Length L Ch R = 1 ,8963    ,248.9,250.7,248.7
XS GIS Cut Line= 4
2237892.62721649699194.1891927662237767.71572111699327.336610916
2237645.54953332699412.4411462282237554.95438283699556.569794741
#Sta/Elev= 30
       0 2111.44     5.3 2109.41      37  2094.3    70.8  2080.7    97.3 2072.73
   115.6 2068.47   135.7 2064.82   170.2 2061.53   200.8 2055.89   213.8 2054.58
   226.7 2052.34   246.8 2051.83   253.22050.638   255.8 2049.86   264.9 2049.43
   269.8 2049.63   272.6  2050.7   281.3 2054.99   295.6 2054.97   313.6  2058.2
   321.5  2060.4   349.1 2069.97   365.4 2074.36   401.7 2087.14     420 2091.04
   422.9 2092.17   431.5 2097.97   434.5 2099.38   482.1 2118.52   501.7 2128.36
#Mann= 3 ,-1,0
       0      .1       0   253.2    .045       0   272.6      .1       0
Bank Sta=253.2,272.6
XS Rating Curve= 0 ,0
Exp/Cntr(USF)=0,0
Exp/Cntr=0.3,0.1

Type RM Length L Ch R = 1 ,8712    ,348.9,343.8,335.4
XS GIS Cut Line= 4
2237726.53610725699034.9613525042237646.92218712699128.301810589
2237480.83107788699251.8406521712237405.33511914699463.229336656
#Sta/Elev= 30
       0 2120.32    23.1 2110.54    40.6 2102.22    65.7    2092   105.4 2073.47
   108.1  2071.9   116.7 2064.72   126.1 2058.14   131.1 2053.01   137.6 2047.41
   141.1 2045.44     146 2043.95   157.7  2042.9   164.4  2043.9   173.9 2046.07
     191 2045.69   213.9  2047.2   240.8 2045.46   285.4 2046.51   291.1  2047.4
   308.2 2052.44   315.5 2053.97   352.3 2058.32   394.8 2065.26   412.6 2070.42
   434.5 2075.12   462.5 2083.78   489.4 2095.05     519  2109.7   554.1 2125.45
#Mann= 3 ,-1,0
       0      .1       0     146    .045       0   164.4      .1       0
#XS Ineff= 2 , 0
                          215.74         2063.45
Permanent Ineff=
       F       F
Bank Sta=146,164.4
XS Rating Curve= 0 ,0
Exp/Cntr(USF)=0,0
Exp/Cntr=0.3,0.1

Type RM Length L Ch R = 1 ,8369    ,403.7,402.9,401
XS GIS Cut Line= 3
2237403.96246534  698829.06328322237324.34854521698981.427854485
2237250.22524026 699402.83256966
#Sta/Elev= 30
       0 2117.35    27.2 2101.85    36.2 2097.49    54.3 2089.99    81.4  2080.4
    90.4 2076.24    99.4 2074.03   139.2 2061.93   144.6 2059.63     160 2051.42
   175.7  2039.8   187.9 2033.02     192 2031.46     196 2030.69   204.1 2030.64
  208.46 2031.47   216.3 2037.55   228.5  2040.6   248.8 2038.11   269.1 2039.67
   297.6  2039.6     334 2044.42   342.2 2044.81   354.9 2047.42   372.2 2049.28
   403.2 2055.62   520.7 2084.96   549.4 2095.02   577.8  2107.6   599.8  2116.6
#Mann= 3 ,0,0
       0      .1       0     192    .045       0  208.46      .1       0
Bank Sta=192,208.46
XS Rating Curve= 0 ,0
Exp/Cntr(USF)=0,0
Exp/Cntr=0.3,0.1

Type RM Length L Ch R = 1 ,7966    ,162.8,167.5,171.9
XS GIS Cut Line= 3
  2237030.600633698760.4305934322236929.02425215698900.441280559
2236937.26017492699314.982726757
#Sta/Elev= 30
       0 2076.46    25.2 2070.43    53.8 2061.82    70.1  2058.8    91.1 2053.63
    99.6  2050.7   129.4 2043.57   154.1  2035.1   174.6 2026.62   181.7 2025.32
   193.7 2024.67   198.32023.274   205.7 2021.64   212.1 2023.31   225.7 2023.39
   233.7 2022.19   245.7 2023.63   261.7 2022.68   297.7 2022.59   345.7 2024.58
   361.8 2024.33   373.8 2028.08   401.8 2041.43   451.4 2057.38   493.8 2067.68
   501.1 2069.99   509.8 2071.09   541.6 2082.16   569.8 2087.96   587.6 2094.96
#Mann= 3 ,-1,0
       0      .1       0   198.3    .045       0   212.1      .1       0
#XS Ineff= 2 , 0
                           246.1         2039.62
Permanent Ineff=
       F       F
Bank Sta=198.3,212.1
XS Rating Curve= 0 ,0
Exp/Cntr(USF)=0,0
Exp/Cntr=0.3,0.1

Type RM Length L Ch R = 1 ,7798    ,49,47.8,48
XS GIS Cut Line= 4
2236753.75755106698707.4909400392236835.45256116  698884.3471707
2236734.90485642699048.6349382682236788.76969825699227.286663657
#Sta/Elev= 30
       0 2040.68    72.5 2038.27    85.6 2035.77   107.6 2033.75   120.8 2028.18
   125.2 2027.63   138.4 2029.32   164.9 2025.49     193 2023.77   214.5 2019.55
   247.3 2019.44   264.7 2018.19   277.7 2019.57   289.6  2019.3   300.5 2015.17
   305.4 2014.33  318.06 2015.18   331.6 2018.36   345.9 2019.24   360.7 2016.17
     374 2016.41   387.4 2019.06   400.5 2025.36   413.1 2027.15   469.1 2042.41
   500.8 2044.61   513.3 2043.62   534.2 2044.88   555.1 2052.48     574 2062.34
#Mann= 3 ,0,0
       0      .1       0   300.5    .045       0  318.06      .1       0
#XS Ineff= 2 , 0
                          347.21         2028.98
Permanent Ineff=
       F       F
Bank Sta=300.5,318.06
XS Rating Curve= 0 ,0
Exp/Cntr(USF)=0,0
Exp/Cntr=0.3,0.1

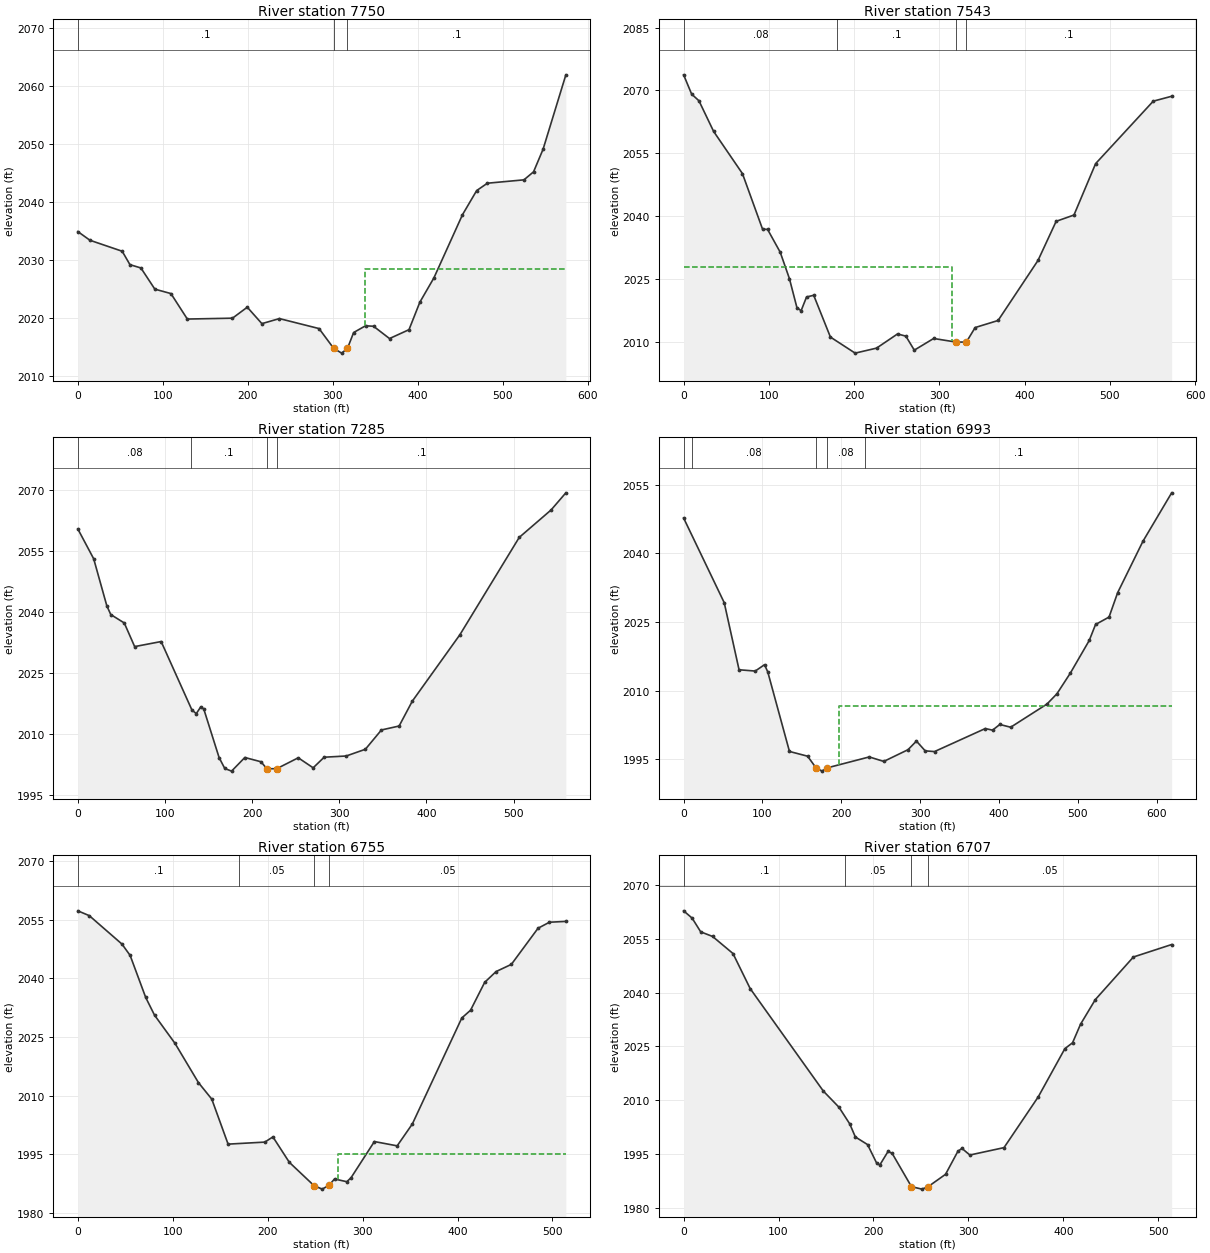
Type RM Length L Ch R = 1 ,7750    ,213.2,207.2,197.1
XS GIS Cut Line= 4
2236706.17694078698717.8150347232236787.87195088698894.671265383
2236687.32424614699058.9590329522236741.18908797 699237.61075834
#Sta/Elev= 30
       0  2034.9    14.3  2033.4    52.2 2031.51    61.3  2029.2    74.2 2028.63
    90.6 2024.98   109.5 2024.22   128.8 2019.83   181.9 2019.98   199.3 2021.87
   216.5 2019.04   237.1 2019.91   283.7 2018.19   300.9 2014.79   310.3 2013.96
  317.13 2014.77   324.4 2017.51   338.4 2018.67   347.8 2018.59   366.6 2016.47
   389.5    2018   402.3 2022.74   418.8 2026.92   452.4  2037.8   469.1 2041.96
   481.7 2043.23   524.7 2043.81     536 2045.19   547.2 2049.08     574  2061.9
#Mann= 3 ,0,0
       0      .1       0   300.9    .045       0  317.13      .1       0
#XS Ineff= 2 , 0
                          338.29         2028.53
Permanent Ineff=
       F       F
Bank Sta=300.9,317.13
XS Rating Curve= 0 ,0
Exp/Cntr(USF)=0,0
Exp/Cntr=0.3,0.1

Type RM Length L Ch R = 1 ,7543    ,260.3,258.3,257.9
XS GIS Cut Line= 3
2236363.20529321698825.0163381232236596.55643843699151.707941419
2236651.46259023699313.681089271
#Sta/Elev= 30
       0 2073.72     9.4 2069.13      18 2067.53    35.2 2060.23      69 2050.18
    92.6 2036.93    98.5 2036.87   113.3 2031.44   124.1 2025.15   132.9 2018.24
   137.8 2017.48   144.2 2020.76   152.6 2021.17   172.2 2011.21   201.2 2007.38
   226.3 2008.57   250.9 2011.95   260.7 2011.43   270.6 2008.09   293.3 2010.87
   319.7 2010.01  331.67 2010.02     342 2013.48   368.9 2015.16   415.7 2029.47
     437  2038.8   457.9  2040.3   483.3 2052.55   550.9 2067.44   572.5 2068.61
#Mann= 4 ,-1,0
       0     .08       0     180      .1       0   319.7    .045       0
  331.67      .1       0
#XS Ineff= 2 , 0
          314.51 2027.98
Permanent Ineff=
       F       F
Bank Sta=319.7,331.67
XS Rating Curve= 0 ,0
Exp/Cntr(USF)=0,0
Exp/Cntr=0.3,0.1

Type RM Length L Ch R = 1 ,7285    ,288,292.1,293.7
XS GIS Cut Line= 3
2236168.57404952699058.0487734012236482.91176865 699301.00849518
2236633.90368614699361.405262176
#Sta/Elev= 30
       0 2060.34    18.2 2053.02    33.3 2041.47    37.8 2039.35    53.3 2037.28
    65.2 2031.49    95.6 2032.73   130.9 2015.95   135.9 2015.06   141.1 2016.74
   144.5 2016.19   162.1 2004.27   168.6 2001.61   176.4 2000.96   191.6  2004.3
   210.1 2003.26   216.9 2001.55  228.14 2001.55   252.9 2004.23     270 2001.77
   282.6 2004.37   307.9 2004.67   329.9 2006.32   348.3 2011.05   368.6 2012.02
   383.7  2018.1   438.4 2034.42   506.4 2058.26   542.9 2064.98   559.9 2069.19
#Mann= 4 ,-1,0
       0     .08       0     130      .1       0   216.9    .045       0
  228.14      .1       0
Bank Sta=216.9,228.14
XS Rating Curve= 0 ,0
Exp/Cntr(USF)=0,0
Exp/Cntr=0.3,0.1

Type RM Length L Ch R = 1 ,6993    ,231.6,237.7,245.8
XS GIS Cut Line= 3
2236049.15316932699224.3875762642236282.50431453699636.183714871
2236279.75900694699781.685017179
#Sta/Elev= 30
       0 2047.69    51.5 2029.19    70.3 2014.54    90.8 2014.26   102.6 2015.65
   106.7 2014.07   134.2  1996.7   157.2 1995.66   167.91993.117   175.6  1992.4
   181.8  1993.1   235.4  1995.5   253.8 1994.52   284.5 1997.08   295.2 1998.96
   306.3 1996.83   318.1 1996.67   382.5  2001.7   391.7 2001.35   400.9 2002.59
   414.7 2001.99   460.7 2007.05   473.3 2009.29   490.3  2013.8   514.3 2020.94
   522.3 2024.43   539.4 2026.05   550.3 2031.37   582.3 2042.58   618.8 2053.19
#Mann= 5 ,-1,0
       0      .1       0      10     .08       0   167.9    .045       0
   181.8     .08       0     230      .1       0
#XS Ineff= 2 , 0
                          196.61         2006.66
Permanent Ineff=
       F       F
Bank Sta=167.9,181.8
XS Rating Curve= 0 ,0
Exp/Cntr(USF)=0,0
Exp/Cntr=0.3,0.1

Type RM Length L Ch R = 1 ,6755    ,47.7,48,47.8
XS GIS Cut Line= 5
2235886.62546934699269.9336018472235964.67730945699468.065195977
2235932.65604171699546.1170360892235932.47759672699597.749408601
2235944.83148087699762.467864044
#Sta/Elev= 30
       0 2057.32    12.1 2056.08    46.5  2048.8    55.1  2045.9    71.5 2035.13
    80.8 2030.59   102.4 2023.35   127.1 2013.29   141.1 2009.08   158.3 1997.54
     197 1998.06   205.5 1999.39   222.8 1992.88   248.7 1986.93   257.4 1986.01
   264.61986.997   270.4 1988.61   283.3 1987.91   287.7 1988.89   312.4  1998.2
   336.4  1997.1   352.4 2002.71   404.5 2029.87   413.7 2031.85   428.6    2039
   440.6 2041.76   456.7  2043.6   484.8 2052.86   496.8  2054.4   514.1 2054.61
#Mann= 4 ,-1,0
       0      .1       0     170     .05       0   248.7    .045       0
   264.6     .05       0
#XS Ineff= 2 , 0
                          273.58         1994.92
Permanent Ineff=
       F       F
Bank Sta=248.7,264.6
XS Rating Curve= 0 ,0
Exp/Cntr(USF)=0,0
Exp/Cntr=0.3,0.1

Type RM Length L Ch R = 1 ,6707    ,433,428.6,422.2
XS GIS Cut Line= 5
2235837.59290311699264.8266434022235915.64474322699462.958237531
2235883.62347548699541.0100776432235883.44503049699592.642450156
2235895.79891465699757.360905599
#Sta/Elev= 30
       0 2062.75       9 2060.71      18  2056.9    30.5 2055.62      52 2050.87
    70.1 2041.12   147.2 2012.58   163.7 2008.08     175 2003.45   180.9 1999.82
   193.8 1997.69   203.5 1992.46   206.7 1992.03   215.4 1995.81   219.7 1995.24
     240 1985.99     251  1985.3   257.2 1985.92   275.9 1989.42   288.9 1995.82
   293.2 1996.64   301.5 1994.79   337.5 1996.85   373.6 2010.99   401.6 2024.39
   409.7 2026.03   418.1 2031.18   433.7 2038.05   473.8  2049.9   514.1 2053.37
#Mann= 4 ,-1,0
       0      .1       0     170     .05       0     240    .045       0
   257.2     .05       0
Bank Sta=240,257.2
XS Rating Curve= 0 ,0
Exp/Cntr(USF)=0,0
Exp/Cntr=0.3,0.1

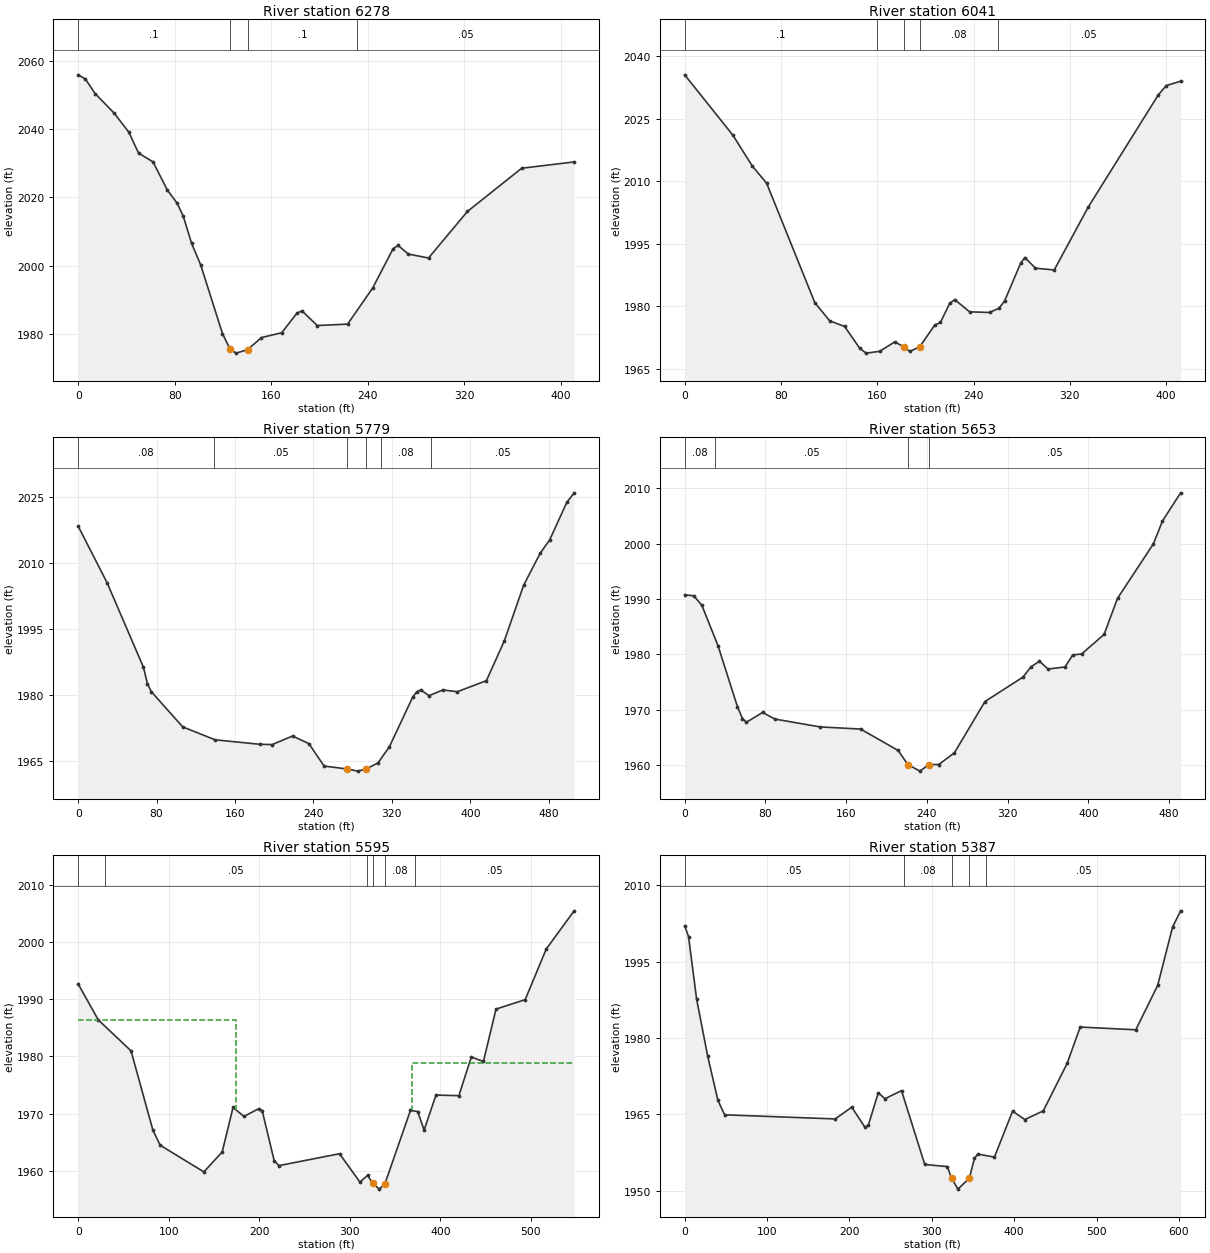
Type RM Length L Ch R = 1 ,6278    ,236.3,237.1,236.4
XS GIS Cut Line= 4
2235483.80236859699303.1779041172235480.46681987699414.362861541
2235541.61854645699607.824687459  2235534.947449699704.555600418
#Sta/Elev= 30
       0 2055.84       6 2054.58      14 2050.36      30 2044.54      42 2039.02
      50 2032.93      62 2030.36      74 2022.04      82 2018.26    87.1 2014.42
      94 2006.49   101.5 2000.22   119.6 1980.06     126 1975.44     131 1974.36
   140.5  1975.4   151.9 1978.92   168.7 1980.33   181.3 1986.06   185.5 1986.74
   198.1 1982.44   223.3 1982.85   244.2 1993.49     261 2004.92   265.2  2005.9
   273.6 2003.37   290.4 2002.21   322.6 2015.83   367.6 2028.49   411.1 2030.34
#Mann= 4 ,-1,0
       0      .1       0     126    .045       0   140.5      .1       0
  231.23     .05       0
Bank Sta=126,140.5
XS Rating Curve= 0 ,0
Exp/Cntr(USF)=0,0
Exp/Cntr=0.3,0.1

Type RM Length L Ch R = 1 ,6041    ,261.8,262.9,262.6
XS GIS Cut Line= 4
2235267.17765067699365.1089049422235264.17565682699475.182012792
2235307.20423534699630.2850283982235379.25208775699751.365447033
#Sta/Elev= 30
       0 2035.58    40.1 2021.06    56.1 2013.71    68.1 2009.54   108.1 1980.88
   120.5  1976.5   132.9 1975.15   145.4 1969.92   150.7 1968.75     162 1969.18
   174.5 1971.45   181.9 1970.29   186.9 1969.15   195.2 1970.26   207.7 1975.47
   212.5 1976.14   220.1 1980.68   224.3 1981.61   236.7 1978.67   253.3 1978.51
   261.2 1979.54   265.8  1981.3   279.1 1990.34   282.6 1991.71   291.4 1989.15
     307 1988.72   335.2  2003.8   393.5 2030.78   400.1    2033     412 2034.04
#Mann= 5 ,-1,0
       0      .1       0  160.11     .08       0   181.9    .045       0
   195.2     .08       0  260.11     .05       0
Bank Sta=181.9,195.2
XS Rating Curve= 0 ,0
Exp/Cntr(USF)=0,0
Exp/Cntr=0.3,0.1

Type RM Length L Ch R = 1 ,5779    ,131.9,125.8,111.5
XS GIS Cut Line= 4
2235032.77585473699386.6368207242235034.57134946699495.264251739
2235092.02718074699699.0529033122235254.51945358699788.827639689
#Sta/Elev= 30
       0 2018.34    29.5  2005.5    66.6  1986.3    70.6 1982.59    74.6 1980.78
   106.6 1972.79   139.7 1969.85   185.4 1968.83   197.9 1968.77   218.7 1970.71
   235.3    1969   250.9 1963.89   274.51963.227   285.2 1962.74  293.88 1963.23
     306 1964.63   317.5 1968.28   341.3 1979.56   345.6 1980.79   349.6 1981.18
   357.9 1979.87   372.1 1981.18   386.8 1980.77   416.5 1983.29   434.8 1992.35
   454.5 2004.97   471.4 2012.24     481 2015.24   498.5 2023.77     506 2025.94
#Mann= 6 ,-1,0
       0     .08       0  138.64     .05       0   274.5    .045       0
  293.88     .05       0  308.64     .08       0  360.38     .05       0
Bank Sta=274.5,293.88
XS Rating Curve= 0 ,0
Exp/Cntr(USF)=0,0
Exp/Cntr=0.3,0.1

Type RM Length L Ch R = 1 ,5653    ,57.4,57.2,57.3
XS GIS Cut Line= 5
2234888.92642551699492.1933112782234900.93440091699644.294333034
2235075.05004424699711.338862361 2235114.0759643699732.352819314
2235161.10720129699829.417287145
#Sta/Elev= 30
       0 1990.77       9 1990.58      17 1988.87    33.1 1981.52    52.3 1970.53
    57.2 1968.41    61.2 1967.73    77.2 1969.51    89.3 1968.31   134.1 1966.89
   174.3  1966.5   211.5 1962.63   221.1 1960.07   233.2  1958.9   241.8 1960.09
   251.7 1960.09   267.2 1962.21   297.5 1971.48   335.3 1975.91     343 1977.74
   351.5 1978.77   359.9 1977.35   376.8 1977.72   384.4 1979.88   393.3 1980.08
   415.5  1983.6   428.8 1990.13   464.4 1999.99   473.3 2004.09   491.3 2009.19
#Mann= 4 ,-1,0
       0     .08       0      30     .05       0   221.1    .045       0
   241.8     .05       0
Bank Sta=221.1,241.8
XS Rating Curve= 0 ,0
Exp/Cntr(USF)=0,0
Exp/Cntr=0.3,0.1

Type RM Length L Ch R = 1 ,5595    ,199.8,208.9,215.7
XS GIS Cut Line= 6
2234815.87790848699499.1979635952234838.89319467699714.340856211
2234910.94104708699710.3381977442234989.99355181699738.356807015
 2235049.0327642699770.3780747532235104.06931813699863.439884117
#Sta/Elev= 30
       0 1992.65    22.1 1986.39    58.3 1980.97    82.5 1967.09    90.5 1964.47
   138.8  1959.8     159 1963.29     171 1971.07   183.1  1969.5   199.2 1970.85
   203.2  1970.5   216.4 1961.77   221.7  1960.9   288.6 1962.98   311.1 1958.03
   319.6 1959.18   325.4 1957.78   332.5 1956.79   338.7 1957.72   366.9 1970.55
   374.9 1970.36     382 1967.11   395.1 1973.24   420.4 1973.13   434.1 1979.89
   447.5 1979.11   461.4 1988.27   493.6 1989.92   516.9 1998.78   547.7 2005.45
#Mann= 6 ,-1,0
       0     .08       0      30     .05       0  318.56     .08       0
   325.4    .045       0   338.7     .08       0  372.43     .05       0
#XS Ineff= 2 , 0
          174.72 1986.44  368.23         1978.86
Permanent Ineff=
       F       F
Bank Sta=325.4,338.7
XS Rating Curve= 0 ,0
Exp/Cntr(USF)=0,0
Exp/Cntr=0.3,0.1

Type RM Length L Ch R = 1 ,5387    ,110.8,112.4,112.3
XS GIS Cut Line= 4
2234766.84534226699458.1707143062234742.82939146 699551.23252367
2234778.85331766699855.4345671822234956.97161946699945.494382696
#Sta/Elev= 30
       0 2002.04     4.7 1999.89    14.5 1987.62    27.9 1976.47    40.3 1967.78
    48.5 1964.93   182.7 1964.12   202.8 1966.43   218.9 1962.47   222.9 1962.87
     235 1969.25   243.1 1968.09   263.2 1969.67   291.4 1955.19   318.8 1954.77
   323.91952.525   331.7 1950.35   345.6 1952.52   351.8 1956.43   355.9 1957.23
     376 1956.63     398 1965.64   412.9    1964   435.3  1965.7   464.3 1975.03
   480.1 1982.15   547.6 1981.61   574.2 1990.34   592.2 2001.75     602 2004.95
#Mann= 5 ,-1,0
       0     .05       0  266.11     .08       0   323.9    .045       0
   345.6     .08       0  366.11     .05       0
Bank Sta=323.9,345.6
XS Rating Curve= 0 ,0
Exp/Cntr(USF)=0,0
Exp/Cntr=0.3,0.1

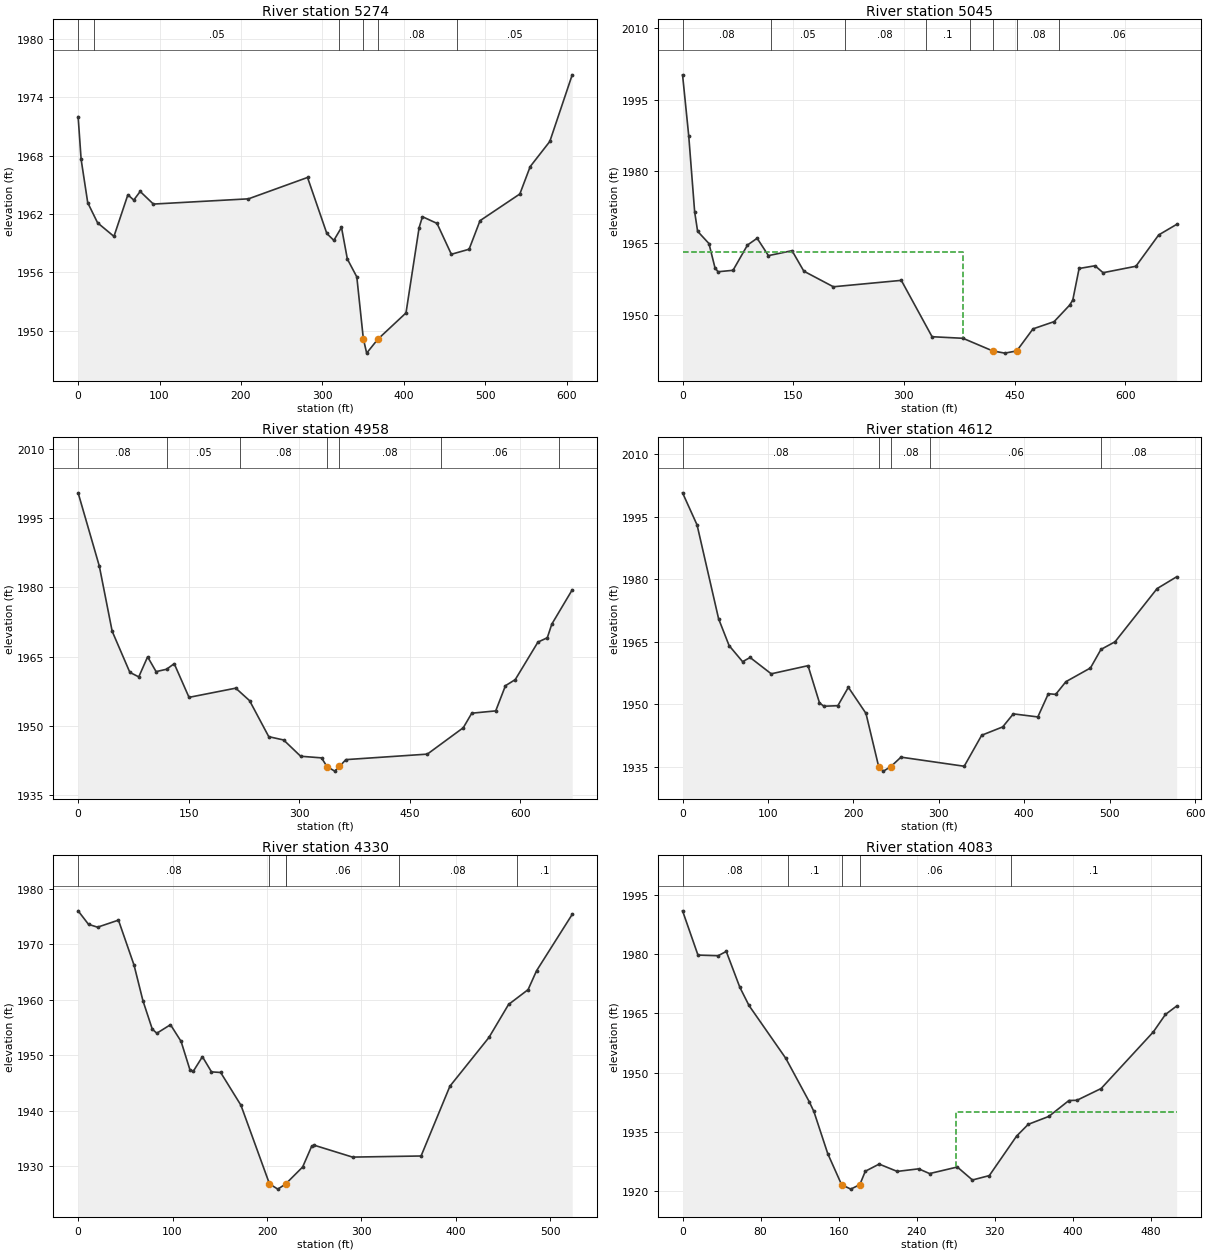
Type RM Length L Ch R = 1 ,5274    ,214.5,229,250.7
BEGIN DESCRIPTION:
Structure XS 4
END DESCRIPTION:
XS GIS Cut Line= 3
2234619.85767997699409.4881242492234672.24221621699841.290594224
2234797.89534224699958.351273505
#Sta/Elev= 30
       0 1972.02     3.7 1967.62    11.8 1963.16    23.9 1961.09      44 1959.69
    61.1 1963.98    68.3 1963.43    76.2 1964.32    92.4 1963.02   209.2 1963.56
   281.7 1965.76   305.4 1959.99     314 1959.28   323.4 1960.62   330.6 1957.36
   342.2 1955.52   350.2 1949.17   354.3 1947.67     368  1949.1   402.6 1951.81
   418.7 1960.59   422.8 1961.72   440.7 1961.03   458.3 1957.85   480.1 1958.37
   493.5 1961.31   542.4 1964.06   555.1 1966.88   579.2 1969.47   606.7 1976.33
#Mann= 6 ,-1,0
       0     .08       0      20     .05       0     320     .08       0
   350.2    .045       0     368     .08       0  464.97     .05       0
Bank Sta=350.2,368
XS Rating Curve= 0 ,0
Exp/Cntr(USF)=0,0
Exp/Cntr=0.3,0.1

Type RM Length L Ch R = 1 ,5045    ,86.5,87.2,88.9
BEGIN DESCRIPTION:
Structure XS 3
END DESCRIPTION:
XS GIS Cut Line= 5
2234577.53469322699408.7718934392234571.62366101699708.017898975
 2234491.8247262699750.1340034582234390.59829964699815.894236774
2234330.74909853699963.670041977
#Sta/Elev= 30
       0 2000.17     8.4 1987.38    16.4 1971.53    20.4 1967.47    35.8  1964.9
    43.9 1959.87      48 1959.01    68.4 1959.31      88 1964.59   101.1 1966.01
   116.4 1962.38   148.4 1963.41   164.4 1959.13   204.4 1955.87   296.5 1957.21
   338.2 1945.43   380.1  1945.1   420.4 1942.46   436.8    1942  452.93 1942.46
     475 1947.07   503.6 1948.58   524.6 1952.02   528.9 1953.08   537.5 1959.69
   559.1 1960.26     570 1958.81   614.5 1960.16   645.4 1966.71   669.7 1968.91
#Mann= 8 ,-1,0
       0     .08       0     120     .05       0     220     .08       0
   329.3      .1       0   389.3     .08       0   420.4    .045       0
  452.93     .08       0  510.25     .06       0
#XS Ineff= 2 , 0
          379.57 1963.17
Permanent Ineff=
       F       F
Bank Sta=420.4,452.93
XS Rating Curve= 0 ,0
Exp/Cntr(USF)=0,0
Exp/Cntr=0.3,0.1

Type RM Length L Ch R = 1 ,4958    ,351.2,345.8,338
BEGIN DESCRIPTION:
Structure XS 2
END DESCRIPTION:
XS GIS Cut Line= 6
2234523.68384037699407.1368188482234505.99722149699639.210370429
2234381.73175132699715.4066892352234339.61564684 699733.13978586
2234313.02069966699740.9452660642234221.65195619 699939.41452039
#Sta/Elev= 30
       0 2000.49    28.8 1984.61    46.2 1970.53    70.2 1961.63    82.3 1960.65
    94.3 1964.99   105.8 1961.79     120  1962.3   130.4 1963.51   150.5 1956.22
   213.9 1958.21   232.7  1955.5   258.7 1947.71   278.9 1946.99     302 1943.47
   330.3 1943.12   337.71941.246   348.2 1940.25   354.6 1941.26   363.4 1942.74
   473.9 1943.93   522.7 1949.65   534.2 1952.79   566.7 1953.29   579.9 1958.74
   593.2 1960.06     624 1968.18   636.7 1969.12   642.8 1972.07   670.5 1979.49
#Mann= 7 ,-1,0
       0     .08       0     120     .05       0     220     .08       0
   337.7    .045       0   354.6     .08       0  491.98     .06       0
  651.98     .08       0
Bank Sta=337.7,354.6
XS Rating Curve= 0 ,0
Exp/Cntr(USF)=0,0
Exp/Cntr=0.3,0.1

Type RM Length L Ch R = 1 ,4612    ,278.3,282,284.3
BEGIN DESCRIPTION:
Structure XS 1
END DESCRIPTION:
XS GIS Cut Line= 2
2234231.48977226699344.0949479892234100.40270746699907.469127257
#Sta/Elev= 30
       0 2000.71      17 1993.01    42.2 1970.53    54.5  1964.1    70.3 1960.25
    79.1 1961.25   103.8 1957.34   146.9 1959.29   160.3 1950.38   165.4 1949.57
   181.8  1949.7   194.1 1954.11   214.7 1947.86   229.61935.094   235.2 1934.02
   243.7 1935.09   255.7 1937.37   329.7 1935.19   350.2 1942.62   374.8 1944.62
   387.2 1947.74   415.9 1947.01   428.2 1952.57   436.8 1952.41   448.8 1955.46
   477.5 1958.74   489.8 1963.18   506.3 1965.02   555.5 1977.76   578.4 1980.59
#Mann= 5 ,-1,0
       0     .08       0   229.6    .045       0   243.7     .08       0
     290     .06       0     490     .08       0
Bank Sta=229.6,243.7
XS Rating Curve= 0 ,0
Exp/Cntr(USF)=0,0
Exp/Cntr=0.3,0.1

Type RM Length L Ch R = 1 ,4330    ,248,247.8,247.5
XS GIS Cut Line= 3
2234038.36150122699344.094947989 2233829.2225963699654.300979202
2233791.19734086699798.396684024
#Sta/Elev= 30
       0 1976.06      11 1973.62    20.6 1973.11    42.7 1974.38    59.2 1966.27
    68.6 1959.85    78.5 1954.72    83.3 1953.97    97.8 1955.51     109  1952.5
   118.4 1947.36   121.9  1947.1   131.6 1949.74   141.2    1947   150.9 1946.89
   172.4 1940.97   202.61926.786   211.4 1925.84   219.61926.753   237.7 1929.83
   247.3 1933.59   250.2 1933.75   290.5 1931.62   363.1 1931.82   393.6 1944.41
     435 1953.22   455.7 1959.16   476.4 1961.84   485.3 1965.23   523.1 1975.42
#Mann= 6 ,-1,0
       0     .08       0   202.6    .045       0   219.6     .08       0
     220     .06       0     340     .08       0  464.12      .1       0
Bank Sta=202.6,219.6
XS Rating Curve= 0 ,0
Exp/Cntr(USF)=0,0
Exp/Cntr=0.3,0.1

Type RM Length L Ch R = 1 ,4083    ,359.3,351.1,336.6
XS GIS Cut Line= 4
2233792.19800548699234.0218401392233779.18936546699280.052412512
2233624.08634986699523.2139143992233583.05910057699688.323576174
#Sta/Elev= 30
       0 1990.91    15.8 1979.72    36.5 1979.56    44.8 1980.65    58.7 1971.59
    68.1 1966.98   105.9 1953.59   129.8 1942.68   134.6 1940.19   148.8 1929.54
     163 1921.69   172.4 1920.56   181.71921.701   187.3 1925.08   201.5 1926.89
     220 1925.04     242 1925.69   253.2 1924.49   281.6 1926.15   297.1 1922.87
   314.4 1923.98   342.4 1933.98   354.3 1936.94   375.4 1938.94     396 1942.96
   404.2 1943.02     429 1945.99   482.5  1960.3   494.9 1964.71   506.4 1966.84
#Mann= 5 ,-1,0
       0     .08       0  107.83      .1       0     163    .045       0
   181.7     .06       0  336.25      .1       0
#XS Ineff= 2 , 0
                          279.86         1940.14
Permanent Ineff=
       F       F
Bank Sta=163,181.7
XS Rating Curve= 0 ,0
Exp/Cntr(USF)=0,0
Exp/Cntr=0.3,0.1