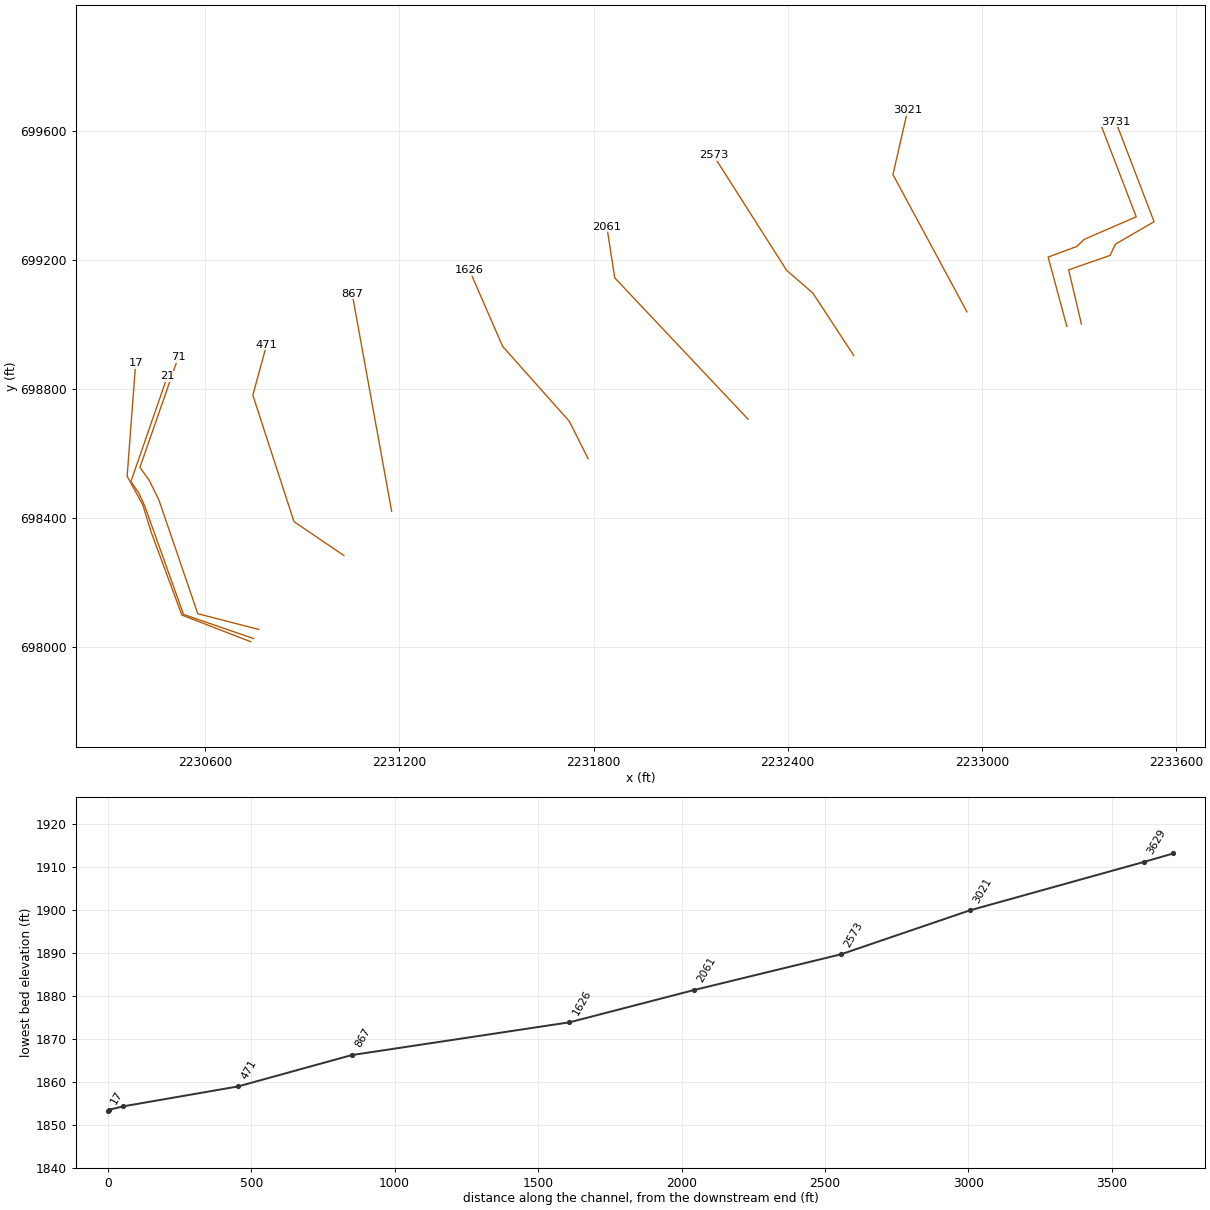
HEC-RAS study BROOKRN.prj: BROOKRN

--- BROOKRN.g01 (geometry) --- (continued)

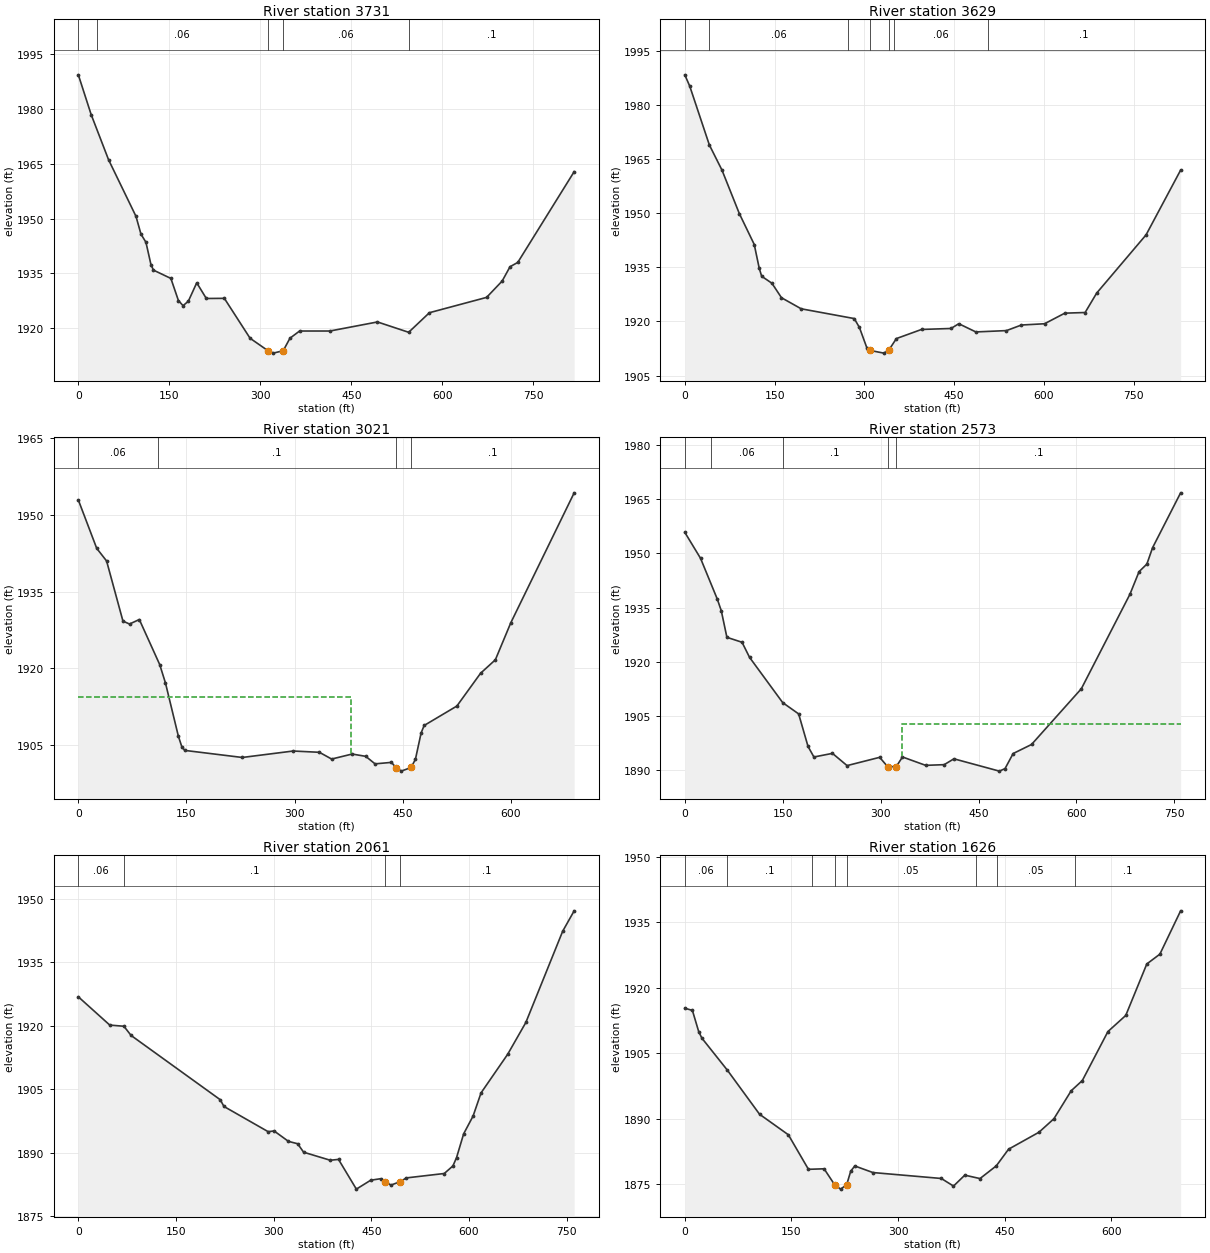
Type RM Length L Ch R = 1 ,3731    ,114.8,102.6,101.1
BEGIN DESCRIPTION:
Structure XS 3
END DESCRIPTION:
XS GIS Cut Line= 6
2233307.40627741699000.674377773 2233268.0141141699168.747607877
2233396.03864485699213.3920596232233412.45204622699248.188470543
2233531.94160825699317.7812923832233413.39767401699627.936774797
#Sta/Elev= 30
       0 1989.35    21.1 1978.49    49.8 1966.12      95 1950.63   103.2 1945.76
   111.4 1943.53   119.7  1937.4   123.8 1935.91   152.5 1933.64   164.9 1927.59
   172.6 1926.18   181.3 1927.42   195.1 1932.44   210.9 1928.15   240.6 1928.19
     283 1917.27   312.4 1913.87   321.2  1913.2   337.61913.856   348.7 1917.28
   364.6 1919.25   414.5 1919.25   492.9 1921.73   544.3  1918.9   578.5 1924.26
   672.7 1928.45   698.4 1932.93   711.3 1936.84   724.1 1938.02     817 1962.85
#Mann= 5 ,-1,0
       0     .08       0      30     .06       0   312.4    .045       0
   337.6     .06       0  544.96      .1       0
Bank Sta=312.4,337.6
XS Rating Curve= 0 ,0
Exp/Cntr(USF)=0,0
Exp/Cntr=0.3,0.1

Type RM Length L Ch R = 1 ,3629    ,588.1,608.3,622.2
BEGIN DESCRIPTION:
Structure XS 2
END DESCRIPTION:
XS GIS Cut Line= 6
2233262.52262941698993.2118467212233204.55681398699208.183679221
2233292.83791669699240.9179404022233316.23303993699263.142902909
2233476.79257962 699332.881621652233368.02549178699616.606999115
#Sta/Elev= 30
       0 1988.44     8.3 1985.28      41 1968.99    62.1    1962    91.1 1949.93
     116 1941.36   124.3 1934.77   128.4 1932.55   145.5 1930.61   161.5 1926.59
   194.4 1923.52     283 1920.81   291.6 1918.36     304 1912.72  309.32 1911.97
   332.4 1911.22   340.4 1911.97   353.4 1915.26   395.4 1917.79   444.6 1918.06
   457.6 1919.38   486.1  1917.1   537.2 1917.47   562.2 1919.02   600.8 1919.37
   634.7 1922.31   668.6 1922.49   687.9 1927.88   770.4 1944.04   828.1    1962
#Mann= 7 ,-1,0
       0     .08       0      40     .06       0  272.65      .1       0
  309.32    .045       0   340.4      .1       0  349.07     .06       0
  505.67      .1       0
Bank Sta=309.32,340.4
XS Rating Curve= 0 ,0
Exp/Cntr(USF)=0,0
Exp/Cntr=0.3,0.1

Type RM Length L Ch R = 1 ,3021    ,443.6,447.4,450.1
BEGIN DESCRIPTION:
Structure XS 1
END DESCRIPTION:
XS GIS Cut Line= 3
 2232953.6486108699038.6780868022232725.10175388699463.651701846
2232770.81112526 699663.78462521
#Sta/Elev= 30
       0  1952.9    25.5 1943.45    39.2 1940.98    61.9 1929.23      71 1928.66
    84.6 1929.54   112.9 1920.73   120.9 1917.12   138.8 1906.72   143.6 1904.65
   147.7 1903.96   227.4 1902.58   298.1 1903.84   334.4 1903.59   351.4 1902.27
   379.8 1903.25   398.7  1902.8   411.6 1901.33   434.3 1901.62   440.7 1900.61
   447.9 1899.91   461.6 1900.62   467.6 1902.22   475.5 1907.37   479.7 1908.83
   525.1 1912.63     558 1919.04   578.5 1921.67   599.9  1928.9   687.8  1954.3
#Mann= 4 ,-1,0
       0     .06       0     110      .1       0   440.7    .045       0
   461.6      .1       0
#XS Ineff= 2 , 0
          378.05 1914.38
Permanent Ineff=
       F       F
Bank Sta=440.7,461.6
XS Rating Curve= 0 ,0
Exp/Cntr(USF)=0,0
Exp/Cntr=0.3,0.1

Type RM Length L Ch R = 1 ,2573    ,506,512.7,510.6
XS GIS Cut Line= 4
2232603.85193857698903.5427953292232477.93771964 699096.39656516
2232396.33248428699167.4981563692232170.60363651699522.943722868
#Sta/Elev= 30
       0 1955.85    24.1 1948.66    49.7 1937.39    55.9 1934.13    64.5 1926.77
    87.7  1925.4    99.2 1921.22     150 1908.68   174.4 1905.56   188.8 1896.54
   197.8 1893.62   226.2 1894.63   248.6 1891.24   298.5 1893.53   310.7 1890.96
  323.93 1890.96   333.5 1893.63     369 1891.31   397.4  1891.5   412.3 1893.12
   481.9 1889.71   490.6 1890.41     503 1894.58   531.2 1897.09   607.5 1912.53
   681.9 1938.68   695.9 1944.95   707.9 1947.06   716.6 1951.58   759.6 1966.79
#Mann= 5 ,-1,0
       0      .1       0      40     .06       0     150      .1       0
   310.7    .045       0  323.93      .1       0
#XS Ineff= 2 , 0
                          333.23         1902.74
Permanent Ineff=
       F       F
Bank Sta=310.7,323.93
XS Rating Curve= 0 ,0
Exp/Cntr(USF)=0,0
Exp/Cntr=0.3,0.1

Type RM Length L Ch R = 1 ,2061    ,433.2,434.5,432.5
XS GIS Cut Line= 3
2232277.26582729698706.1603307312231865.46968868699143.884374362
2231841.06695454699302.502146271
#Sta/Elev= 30
       0  1926.8    48.3 1920.12      70 1919.85      81 1917.68     218 1902.49
   223.6 1900.91   291.5 1894.95   300.7 1895.12   322.7 1892.66   336.8  1892.1
     346  1890.1   386.9  1888.2   399.6  1888.4     427 1881.38     449 1883.48
   464.2 1883.84     471 1883.13   480.3 1882.34   494.21883.145   503.8 1884.03
     562 1885.07   575.3 1886.86   580.8 1888.79   591.8 1894.45   606.3 1898.65
   618.5 1904.11   659.4 1913.23   687.3 1920.74   743.9  1942.3   761.5 1947.11
#Mann= 4 ,-1,0
       0     .06       0      70      .1       0     471    .045       0
   494.2      .1       0
Bank Sta=471,494.2
XS Rating Curve= 0 ,0
Exp/Cntr(USF)=0,0
Exp/Cntr=0.3,0.1

Type RM Length L Ch R = 1 ,1626    ,759.4,758.6,750.2
XS GIS Cut Line= 4
2231783.20705125698583.6523723652231725.36468971698699.322685932
2231519.27588958698931.3133571092231416.41660071699167.991074172
#Sta/Elev= 30
       0 1915.32    10.7 1914.82    19.6 1909.94    24.1 1908.45      60  1901.1
   105.2 1891.02   145.7 1886.32     174  1878.4     196 1878.52   210.8 1874.88
   219.3 1873.86   227.8 1874.88   233.5 1877.98   239.2 1879.17   264.7 1877.66
     361  1876.3   378.1 1874.56     394 1877.06   415.4 1876.28   438.3 1879.19
   455.6 1883.01   498.4  1886.9   519.4 1889.99   543.7  1896.4   559.4 1898.75
   595.4 1909.97   620.5 1913.67   650.1 1925.46   668.5 1927.71   697.7 1937.64
#Mann= 8 ,-1,0
       0     .06       0      60      .1       0  179.33     .05       0
   210.8    .045       0   227.8     .05       0  409.33     .06       0
  439.33     .05       0  549.64      .1       0
Bank Sta=210.8,227.8
XS Rating Curve= 0 ,0
Exp/Cntr(USF)=0,0
Exp/Cntr=0.3,0.1

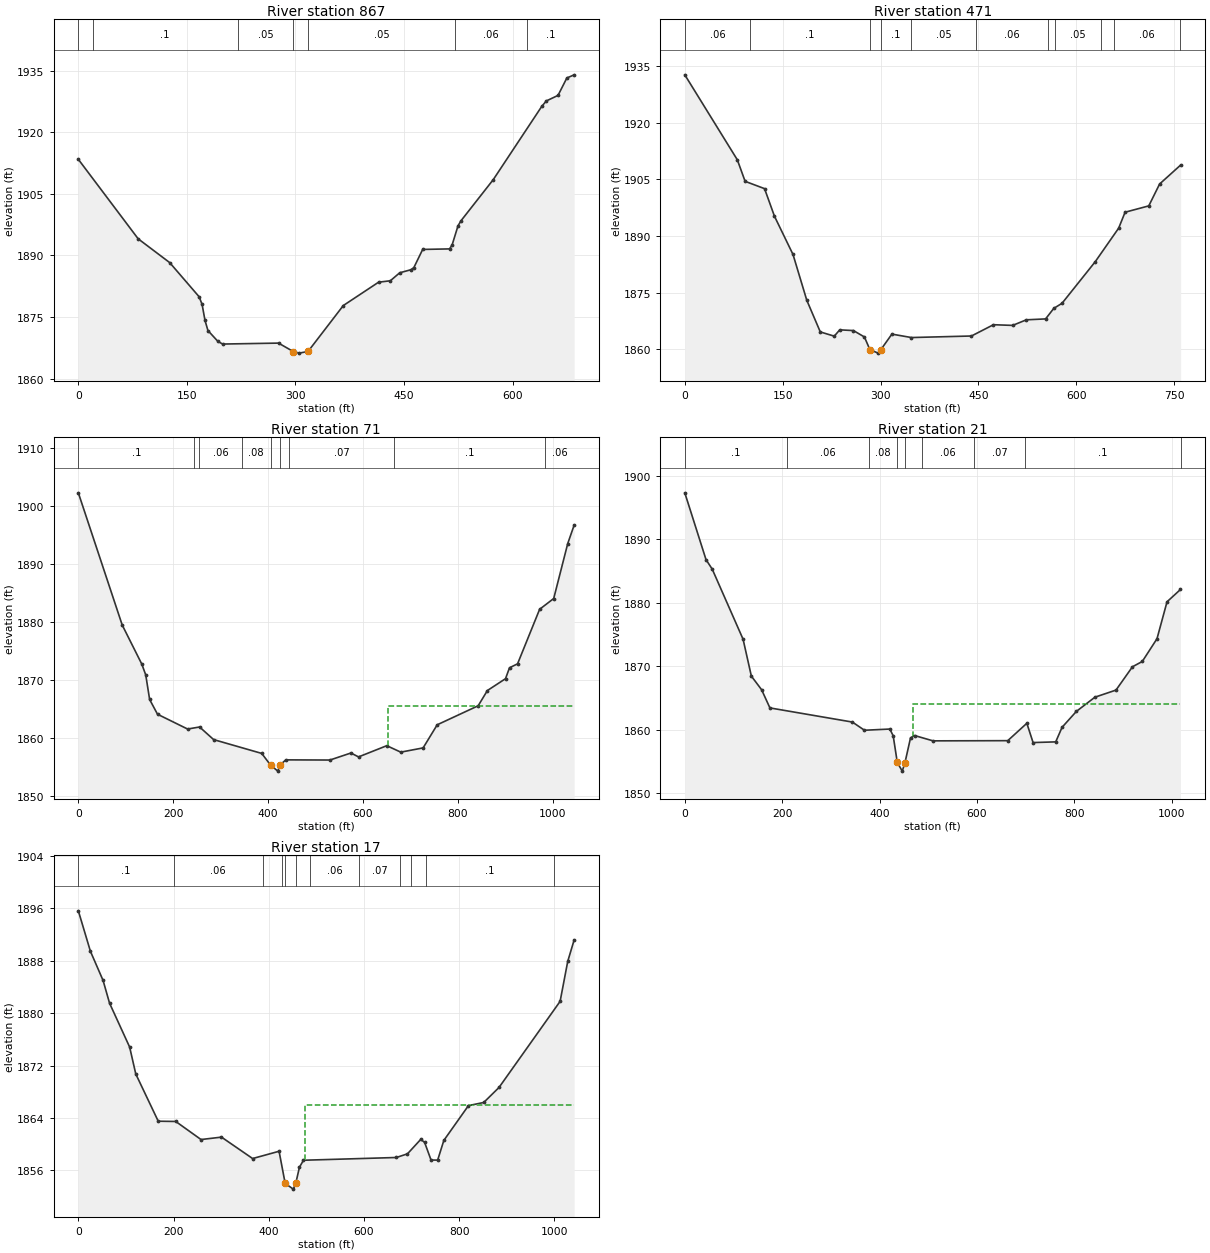
Type RM Length L Ch R = 1 ,867     ,392.5,396.3,396.5
XS GIS Cut Line= 2
2231176.09244923698420.9533754722231054.07877853699095.078906083
#Sta/Elev= 30
       0  1913.4    82.7 1894.05   126.2 1888.27   166.9 1879.95     171  1878.1
     175 1874.21   179.1 1871.72   192.9 1869.08   199.4 1868.44   276.6 1868.67
     297 1866.62   305.1 1866.23   317.41866.635   366.1 1877.81   414.9  1883.5
   431.1 1883.84   444.1 1885.79   459.6 1886.53   463.6 1887.05   475.8 1891.47
     513  1891.6   516.5 1892.58   524.6 1897.21   528.7 1898.44   573.4 1908.48
   640.3 1926.28   646.6 1927.61   662.8 1928.96     675  1933.2   685.1 1933.97
#Mann= 7 ,-1,0
       0     .06       0      20      .1       0     220     .05       0
     297    .045       0   317.4     .05       0     520     .06       0
     620      .1       0
Bank Sta=297,317.4
XS Rating Curve= 0 ,0
Exp/Cntr(USF)=0,0
Exp/Cntr=0.3,0.1

Type RM Length L Ch R = 1 ,471     ,399.4,400.1,399.1
XS GIS Cut Line= 4
2231028.55860608698283.8312630892230874.34688339698388.898590635
2230747.24930974698780.3591174612230789.61516763698936.265474465
#Sta/Elev= 30
       0  1932.7    80.5 1910.17    92.4 1904.47   122.2 1902.53   137.4 1895.21
   165.8 1885.08   186.9 1872.95   207.6 1864.55     229 1863.43   237.4  1865.1
   258.4 1864.91   275.2 1863.21   283.6 1859.86   296.2 1858.93   300.4 1859.85
   317.3 1863.97   347.3 1863.06   439.2 1863.47   472.9 1866.46   502.3 1866.28
   523.3 1867.76   552.8    1868   565.4  1870.8     578 1872.14   628.9 1883.17
   664.8 1892.07   674.6 1896.28   710.9 1897.96   727.5 1903.76   759.7 1908.78
#Mann= 11 ,-1,0
       0     .06       0     100      .1       0   283.6    .045       0
   300.4      .1       0   346.6     .05       0   446.6     .06       0
   556.6      .1       0   566.6     .05       0  638.18      .1       0
  658.18     .06       0  758.18      .1       0
Bank Sta=283.6,300.4
XS Rating Curve= 0 ,0
Exp/Cntr(USF)=0,0
Exp/Cntr=0.3,0.1

Type RM Length L Ch R = 1 ,71      ,49.8,50.2,49.5
XS GIS Cut Line= 6
2230765.71966017698054.7910007042230577.20181319698103.541950544
2230456.80506365698456.2756224812230427.17940065698516.424695852
2230398.36746272698556.7562179392230516.90100072698897.902010059
#Sta/Elev= 30
       0 1902.22    92.5 1879.45   133.8 1872.72   142.1 1870.86   150.3 1866.63
   166.9 1864.09   230.3 1861.54   255.6 1861.89   285.2 1859.72   386.6 1857.34
  405.241855.331   420.5 1854.29   424.81855.328   437.4 1856.23   530.3  1856.2
   574.6 1857.41   590.7 1856.74   650.2 1858.67   679.7 1857.56   726.8 1858.29
   756.5 1862.27   842.9 1865.55   862.3 1868.17   900.5 1870.21   908.9 1872.09
   925.9 1872.77   972.4 1882.16  1002.1 1884.02  1031.7 1893.49  1045.2 1896.66
#Mann= 9 ,-1,0
       0      .1       0  244.72     .07       0  254.72     .06       0
  344.72     .08       0  405.24    .045       0   424.8     .08       0
  444.72     .07       0  664.48      .1       0  984.05     .06       0
#XS Ineff= 2 , 0
                          652.79         1865.48
Permanent Ineff=
       F       F
Bank Sta=405.24,424.8
XS Rating Curve= 0 ,0
Exp/Cntr(USF)=0,0
Exp/Cntr=0.3,0.1

Type RM Length L Ch R = 1 ,21      ,3.9,4,6.6
XS GIS Cut Line= 6
2230749.34430571698026.6328745422230532.99629045 698101.41849793
2230413.29480264698436.8527927352230395.38234544698476.403351891
2230370.58422109 698513.158360342230483.46844635 698839.22047353
#Sta/Elev= 30
       0 1897.34    43.6 1886.81    56.3 1885.32   119.7 1874.27   136.7 1868.46
   157.8 1866.31   174.8 1863.45   344.2 1861.22     369 1859.93   421.1 1860.12
     428 1859.06  436.42 1854.86   446.6 1853.49  452.23 1854.84   463.6 1858.73
   471.9  1859.1   509.8 1858.26   663.3 1858.29   702.5 1861.03   715.3 1857.99
   761.8  1858.1   774.8 1860.39   804.2  1862.9   842.3 1865.14   885.6 1866.26
   919.4 1869.93   939.6 1870.77   969.8 1874.35   990.4 1880.17    1018 1882.11
#Mann= 9 ,-1,0
       0      .1       0     210     .06       0  378.91     .08       0
  436.42    .045       0  452.23      .1       0  486.83     .06       0
  594.73     .07       0  698.82      .1       0 1018.33     .06       0
#XS Ineff= 2 , 0
                           468.4          1864.1
Permanent Ineff=
       F       F
Bank Sta=436.42,452.23
XS Rating Curve= 0 ,0
Exp/Cntr(USF)=0,0
Exp/Cntr=0.3,0.1

Type RM Length L Ch R = 1 ,17      ,,,
XS GIS Cut Line= 6
2230740.65326623698016.8187034752230527.88714102 698099.41146094
2230432.72592046698357.064954336 2230407.2467074698440.628160841
2230358.87542719698529.4246164962230385.14531019698878.656172674
#Sta/Elev= 30
       0 1895.64    25.4 1889.46      52 1885.01    65.6 1881.54   107.8 1874.84
   120.7 1870.73   167.9 1863.52   204.7 1863.48   257.8 1860.72   300.8 1861.09
   366.2 1857.82   421.8 1858.93   434.6 1854.02   451.7 1853.15  456.82 1854.02
   464.6  1856.5   473.1 1857.56   668.2 1857.98   691.6 1858.54   719.4 1860.74
   727.5  1860.3   741.1 1857.59     755 1857.58     768 1860.59   819.7  1865.9
   851.8 1866.38   883.9 1868.67  1012.3 1881.82  1028.3 1887.92  1041.8  1891.2
#Mann= 12 ,-1,0
       0      .1       0     200     .06       0     387     .08       0
     427      .1       0   434.6    .045       0  456.82      .1       0
     487     .06       0  589.39     .07       0  676.89     .06       0
  699.94     .07       0  729.94      .1       0  999.94     .06       0
#XS Ineff= 2 , 0
                          475.84         1865.95
Permanent Ineff=
       F       F
Bank Sta=434.6,456.82
XS Rating Curve= 0 ,0
Exp/Cntr(USF)=0,0
Exp/Cntr=0.3,0.1
LCMann Table=0

Chan Stop Cuts=-1
Use User Specified Reach Order=0
Composite Channel Slope=5